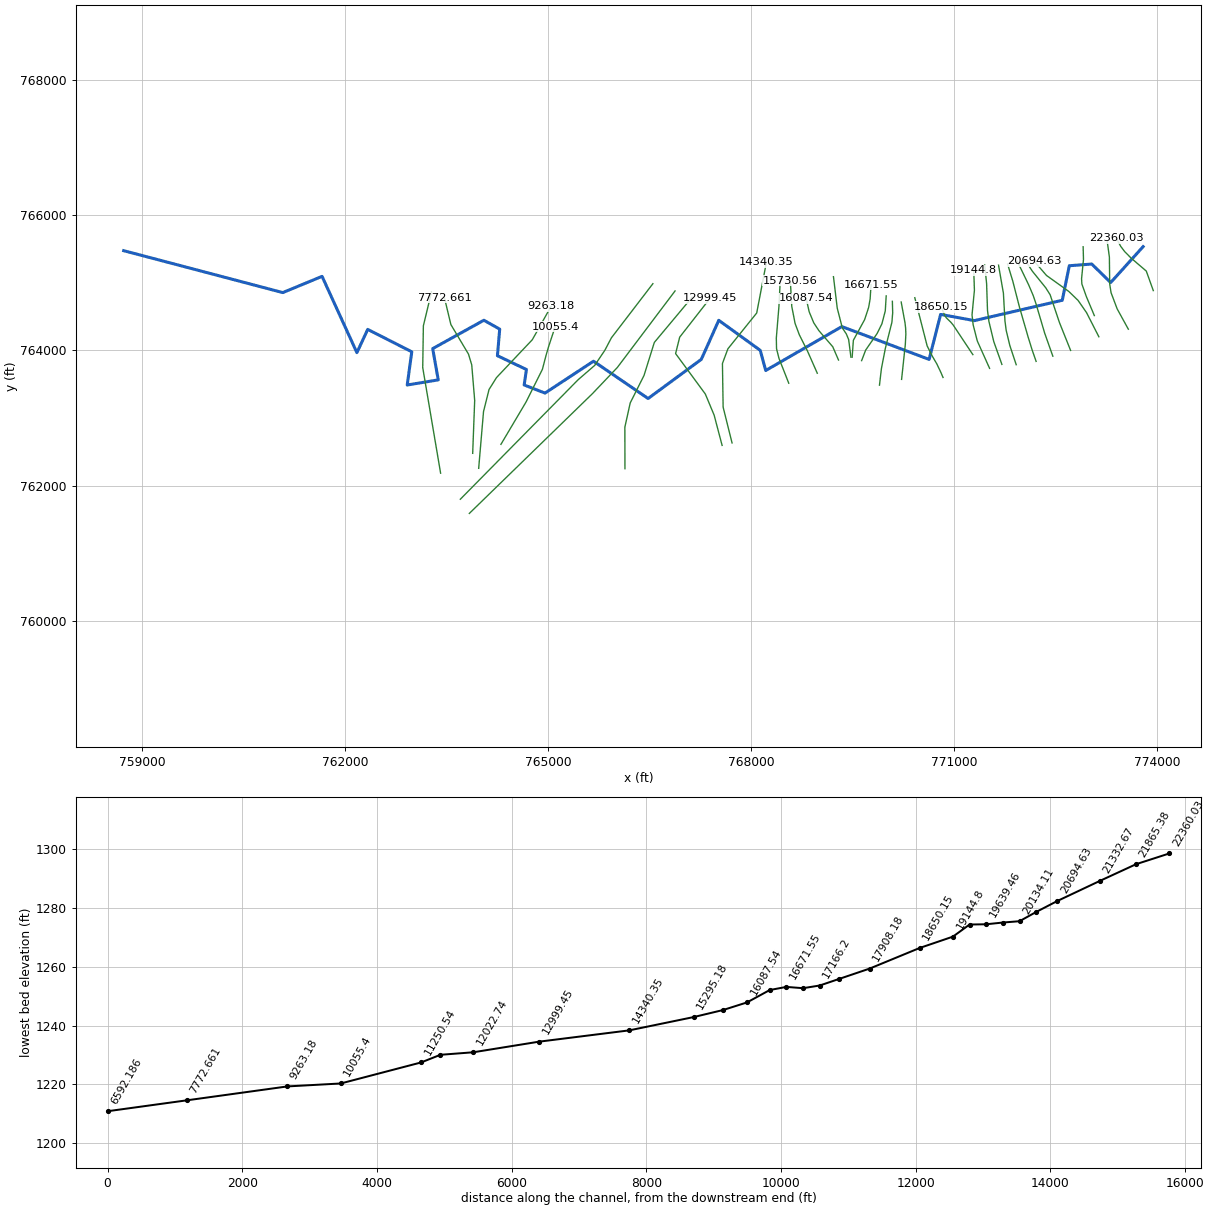
--- 14213_ras.prj (project) ---

Proj Title=14213
Current Plan=p01
Default Exp/Contr=0.3,0.1
English Units
Geom File=g01
Flow File=f01
Plan File=p01
Y Axis Title=Elevation
X Axis Title(PF)=Main Channel Distance
X Axis Title(XS)=Station
BEGIN DESCRIPTION:
RFD model 14213 exported to HEC-RAS
END DESCRIPTION:

--- 14213_ras.p01 (plan) ---

Plan Title=Plan 01
Program Version=4.10
Short Identifier=Plan 01
Geom File=g01
Flow File=f01
Subcritical Flow
Calc Critical at every XS
Secant Critical Depth

--- 14213_ras.f01 (steady flow) ---

Flow Title=Flow 01
Program Version=5.01
Number of Profiles= 6
Profile Names=10yr,25yr,50yr,100yr,100plus,500yr
River Rch & RM=14213,35,22360.03
  3249.9 5311.66 7289.72 9110.8413301.83 15431.9
River Rch & RM=14213,35,21865.38
 3261.65 5332.27 7319.29 9149.2413357.89 15493.1
River Rch & RM=14213,35,21332.67
 3279.22 5363.16 7363.68 9206.92 13442.115585.15
River Rch & RM=14213,35,20694.63
 3290.44 5383.03 7392.35 9244.3113496.6915645.26
River Rch & RM=14213,35,20381.43
 3293.13 5387.82 7399.28 9253.3513509.8915659.84
River Rch & RM=14213,35,20134.11
 3303.45 5406.14 7425.75 9287.9213560.3715715.56
River Rch & RM=14213,35,19886.78
 3308.52 5415.15 7438.77 9304.9313585.1915742.96
River Rch & RM=14213,35,19639.46
 3310.74 5419.09 7444.47 9312.3613596.0515754.94
River Rch & RM=14213,35,19392.13
 3334.41 5461.08 7505.12 9391.5313711.6315882.23
River Rch & RM=14213,35, 19144.8
 3335.97 5463.87 7509.15  9396.813719.3315890.76
River Rch & RM=14213,35,18650.15
 3342.07 5474.82 7525.09 9417.74 13749.915924.86
River Rch & RM=14213,35,17908.18
 3456.87 5675.25 7811.92 9789.24 14292.316509.46
River Rch & RM=14213,35,17457.17
 3462.83 5685.91 7827.41 9809.5514321.9416542.21
River Rch & RM=14213,35, 17166.2
 3470.01 5698.76 7846.05    983414357.6316581.65
River Rch & RM=14213,35,16918.88
  3471.9 5702.19 7851.09 9840.6414367.3416592.55
River Rch & RM=14213,35,16671.55
 3473.49 5705.09 7855.34 9846.2614375.5416601.77
River Rch & RM=14213,35,16424.23
 3625.39  5975.7 8247.2810359.1515124.3517422.09
River Rch & RM=14213,35,16087.54
 3645.07 6011.44 8299.6410428.3215225.3417534.63
River Rch & RM=14213,35,15730.56
 3648.69    6018 8309.2310440.9615243.8117555.14
River Rch & RM=14213,35,15295.18
 3654.15 6027.91 8323.7510460.1415271.8117586.29
River Rch & RM=14213,35,14340.35
 3659.85 6038.37 8339.1610480.5915301.6717619.88
River Rch & RM=14213,35,12999.45
 3869.29 6408.77 8873.6311177.8316319.6418716.25
River Rch & RM=14213,35,12022.74
 3966.35 6581.66  9124.211505.9716798.7119233.27
River Rch & RM=14213,35,11534.38
  4060.2 6753.51 9377.2311841.7517288.96 19776.2
River Rch & RM=14213,35,11250.54
 4062.98 6758.63  9384.811851.85 17303.719792.63
River Rch & RM=14213,35, 10055.4
 4206.71 7017.26 9761.9812348.4618028.7520577.51
River Rch & RM=14213,35, 9263.18
 4211.06 7025.34 9773.9912364.52 18052.2 20603.7
River Rch & RM=14213,35,7772.661
 4306.67 7202.6410037.0512715.9218565.2421174.33
River Rch & RM=14213,35,6592.186
 4352.63    728810163.8512885.4618812.7721449.42
River Rch & RM=14213,35,5288.464
 4386.57 7351.2510257.9913011.5418996.8621654.46
River Rch & RM=14213,35,4294.785
 4389.91  7357.510267.3113024.0519015.1121674.85
River Rch & RM=14213,35,3572.997
 4389.17 7356.1110265.2413021.2719011.0521670.32
River Rch & RM=14213,35,1790.574
 4389.91  7357.510267.3113024.0519015.1121674.85
Boundary for River Rch & Prof#=14213,35,1
Up Type= 0
Dn Type= 2
Boundary for River Rch & Prof#=14213,35,2
Up Type= 0
Dn Type= 2
Boundary for River Rch & Prof#=14213,35,2
Up Type= 0
Dn Type= 2
Boundary for River Rch & Prof#=14213,35,2
Up Type= 0
Dn Type= 2
Boundary for River Rch & Prof#=14213,35,2
Up Type= 0
Dn Type= 2
Boundary for River Rch & Prof#=14213,35,2
Up Type= 0
Dn Type= 2

--- 14213_ras.g01 (geometry) ---

Geom Title=14213
Program Version=4.10

River Reach=14213,35
Reach XY= 30
773797.016196012765532.464418501773317.397209883765001.739518628
773037.883320957765275.350629762772705.938876569765250.350629747
772601.772209823764739.586740866771302.119432122764438.892296404
770803.508320987764530.906185314770633.369432062763865.281185299
769343.213110477764350.676373228768217.344975829 763701.37103495
768136.494432062763999.656185299767523.299987674764443.406185299
 767265.31387651763865.975629777766478.716654271763287.364518657
765671.147209823763838.683963075764954.480543196763367.503407523
764646.147209853763487.295074195 764679.68887651763716.114518642
764250.938876539763919.864518628764284.688876539764313.197851971
764050.522209853764444.447851986763293.855543226764024.864518642
763375.938876569763562.781185314762917.188876569763486.947851971
762984.549987644763977.850629762762333.161098719764309.100629747
762173.268500894763965.075078815761658.257599562765093.148481071
761077.708124518764853.317455828758725.364810824 765472.97520633

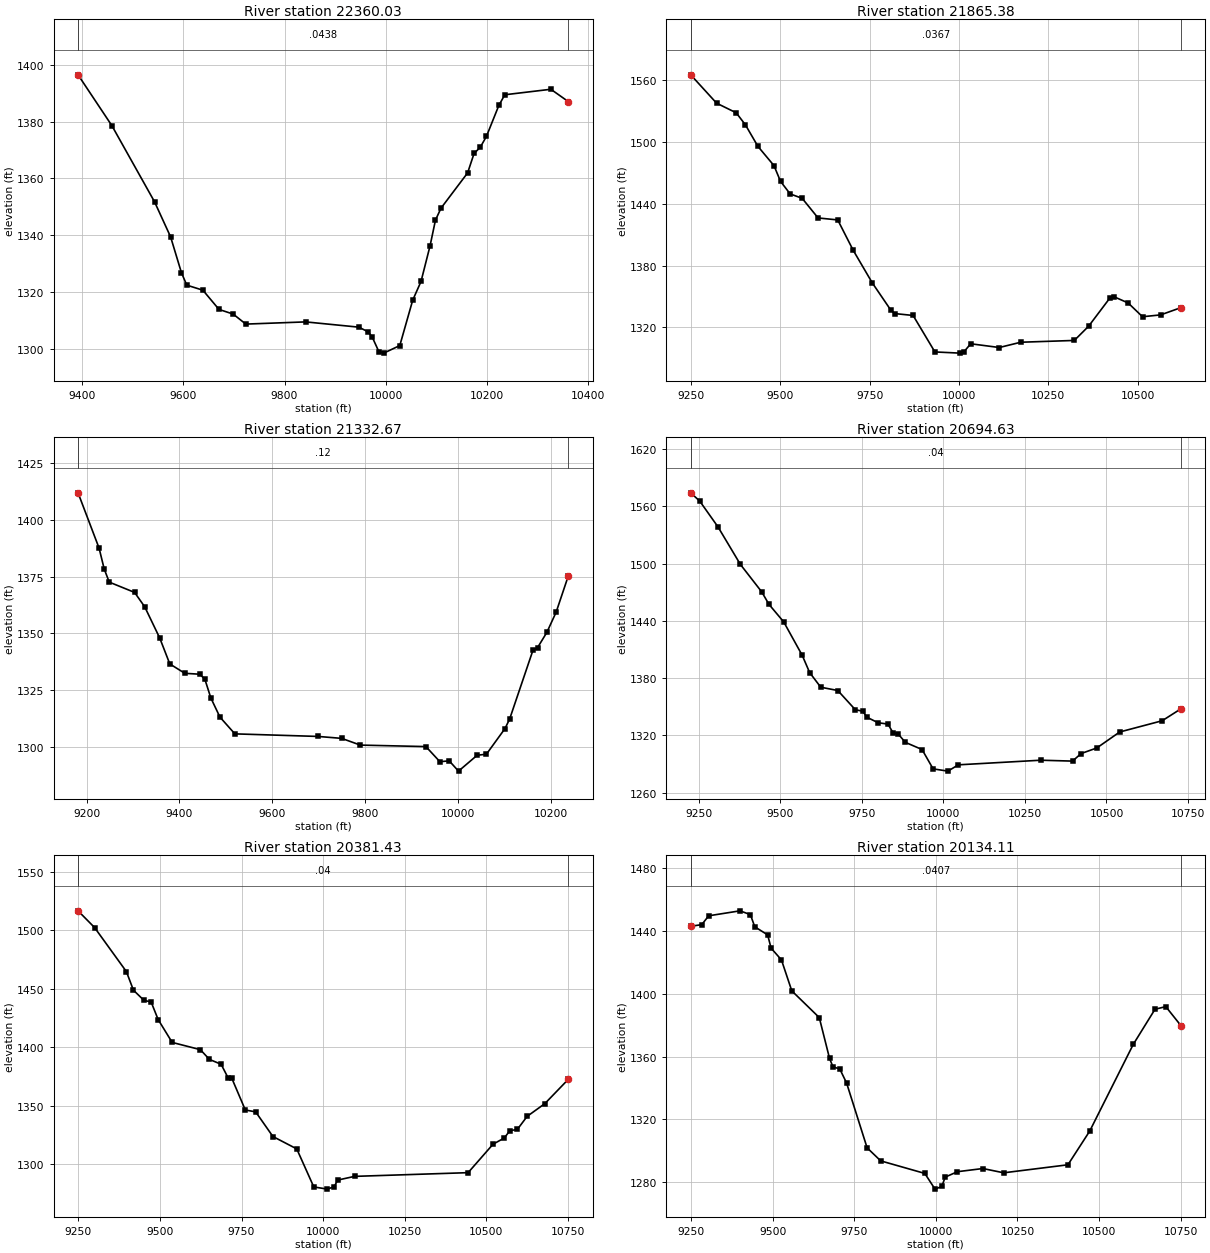
Type RM Length L Ch R = 1 ,22360.03,494.650200,494.650200,494.650200
XS GIS Cut Line= 6
773947.589946061764882.678387165773843.955887089765171.430605875
773621.607086642765361.496503389773524.950552464 765458.78866642
773465.867599767765537.043246435773402.298508346765655.749417196
#Sta/Elev= 30
9391.6821396.4169458.5551378.5689542.8931351.8279574.7661339.4569596.0161326.964
 9606.641322.5279638.5141320.7569670.3871313.9989698.469 1312.369723.4061308.842
9841.8071309.6159947.0521307.7629965.5941306.0929973.3631304.3039986.5181299.174
9996.1351298.64210027.951301.29910053.461317.23210069.921323.82610087.861336.397
10098.481345.37710109.481349.58510162.091361.97210174.781368.78810187.031370.963
10199.281374.78610223.791385.65910235.581389.41110326.661391.34210361.041387.029
#Mann= 3 , 0 , 0
9391.682  0.0438       09391.682  0.0438       010361.04  0.0438       0
#XS Ineff= 2 , 0
       0                               0
Bank Sta=9391.682,10361.04
Exp/Cntr=0.3,0.1

Type RM Length L Ch R = 1 ,21865.38,532.712300,532.712300,532.712300
XS GIS Cut Line= 6
773578.592289731764312.204501147773412.999144972764613.530355694
773323.272222796764851.743343362773303.096583895764980.778147012
773298.442305048765378.072483791773264.970116267765620.880880151
#Sta/Elev= 30
9249.0861565.3979321.5521537.846  9376.51528.4969402.332 1516.739437.3221495.827
9482.1931477.1739500.4541461.9089527.4631449.6839561.0551445.4089605.6351426.323
9660.6761424.4139703.8211394.9959757.3511363.2569809.9241336.4439820.2871333.421
9871.7121331.5649932.6781296.12910002.951294.97610012.96 1295.8310032.961304.068
10112.991300.42910172.991305.56210323.031307.30510363.071321.13610423.271348.842
10433.311349.88810473.631343.73510513.961330.338 10564.61332.12610621.421339.169
#Mann= 3 , 0 , 0
9249.086  0.0367       09249.086  0.0367       010621.42  0.0367       0
#XS Ineff= 2 , 0
       0                               0
Bank Sta=9249.086,10621.42
Exp/Cntr=0.3,0.1

Type RM Length L Ch R = 1 ,21332.67,638.040300,638.040300,638.040300
XS GIS Cut Line= 6
773075.916767167764513.469722938772957.236123712764795.925505669
772891.738433354 764980.20212203772887.237452504765058.329853884
772915.533892803765344.216184008772910.432615644765530.861592898
#Sta/Elev= 30
9181.776 1411.969227.0831387.5629237.9931378.4529248.9021372.6179303.4491368.083
9325.254 1361.749357.6391347.9559379.2291336.5719411.6131332.4359443.9981332.035
9454.7921329.7799467.5611321.5829487.1771313.1379519.2861305.7579698.8041304.617
9749.0511303.774 9789.34 1300.819930.4631300.1519960.555 1293.499980.5841293.874
10000.611289.33910040.671296.32510060.681296.80410100.691308.10210110.691312.314
10160.721342.53310170.731343.75110190.751350.47610210.771359.40110236.781375.267
#Mann= 3 , 0 , 0
9181.776    0.12       09181.776    0.12       010236.78    0.12       0
#XS Ineff= 2 , 0
       0                               0
Bank Sta=9181.776,10236.78
Exp/Cntr=0.3,0.1

Type RM Length L Ch R = 1 ,20694.63,313.197900,313.197900,313.197900
XS GIS Cut Line= 6
773142.743813656 764200.20652544772960.247919518764557.546670306
772836.236295643764736.844976342772698.644273784764869.941358345
772368.167408933765106.928060109772183.717272736765321.328067397
#Sta/Elev= 30
 9226.14 1574.079253.8291565.3779309.6691538.3899378.2971499.0529443.6851470.279
9466.0211457.1229511.0911438.8039567.8141403.7419590.5041385.7229624.5371370.363
9676.7971366.9039730.5461346.748 9752.66 1345.279766.8271338.7729800.2621333.125
9830.3991331.743 9845.761322.7969862.5111321.0569883.7231312.5869934.9451305.052
9968.788 1284.7910014.231282.42610046.041289.02810298.441293.86210395.96 1292.93
10422.331300.86210470.461306.72410540.441323.43810670.621335.22110728.011347.706
#Mann= 3 , 0 , 0
 9226.14    0.04       0 9226.14    0.04       010728.01    0.04       0
#XS Ineff= 2 , 0
       0                               0
Bank Sta=9226.14,10728.01
Exp/Cntr=0.3,0.1

Type RM Length L Ch R = 1 ,20381.43,247.325100,247.325100,247.325100
XS GIS Cut Line= 6
772725.181023854763998.135954363772559.243650985  764412.6529204
772421.968244379764822.565418417772357.388957024764924.265590137
772159.408188628765169.764900806772057.413233692765326.040958856
#Sta/Elev= 30
 9249.031516.6439299.7321502.3139397.1021464.704 9418.741448.7769451.1961440.033
9472.8341438.7879494.4721423.6529537.3981404.1339623.7061397.9479651.6041389.599
9687.3641385.4579708.6211373.8819719.1981374.0899761.5051346.3689793.2361344.742
 9846.091323.6759919.1261313.0819971.2941280.57210013.051278.69410033.981280.862
10044.44 1286.4210096.25  1289.610444.121292.77210520.511317.11510554.991322.398
   105721328.70410594.841329.69110624.961340.89610679.261351.813 10750.9 1372.53
#Mann= 3 , 0 , 0
 9249.03    0.04       0 9249.03    0.04       0 10750.9    0.04       0
#XS Ineff= 2 , 0
       0                               0
Bank Sta=9249.03,10750.9
Exp/Cntr=0.3,0.1

Type RM Length L Ch R = 1 ,20134.11,247.325100,247.325100,247.325100
XS GIS Cut Line= 6
772462.312559067763913.319580546772341.674173361764253.869210763
772212.520818392764691.094109485772173.767305612764805.646418424
772104.656487661764968.183112778771936.708967515765316.947741185
#Sta/Elev= 30
 9249.02 1442.999282.8061443.9949304.1351449.6449400.1171452.8099431.9091450.378
9445.1941442.6659484.7391437.4839495.305 1429.029527.0031421.5589558.7011401.844
9642.9241384.8179674.3281358.8499684.7961353.4429705.7331352.0969726.6691343.109
9789.477 1301.859831.1621293.5419966.3111285.5419997.4991275.542 10018.31277.219
10028.711283.18410066.27 1286.6510144.291288.66310208.041285.93710404.821291.051
10471.581312.524 10605.11367.78210671.58 1390.1110704.681391.79410750.961379.701
#Mann= 3 , 0 , 0
 9249.02  0.0407       0 9249.02  0.0407       010750.96  0.0407       0
#XS Ineff= 2 , 0
       0                               0
Bank Sta=9249.02,10750.96
Exp/Cntr=0.3,0.1

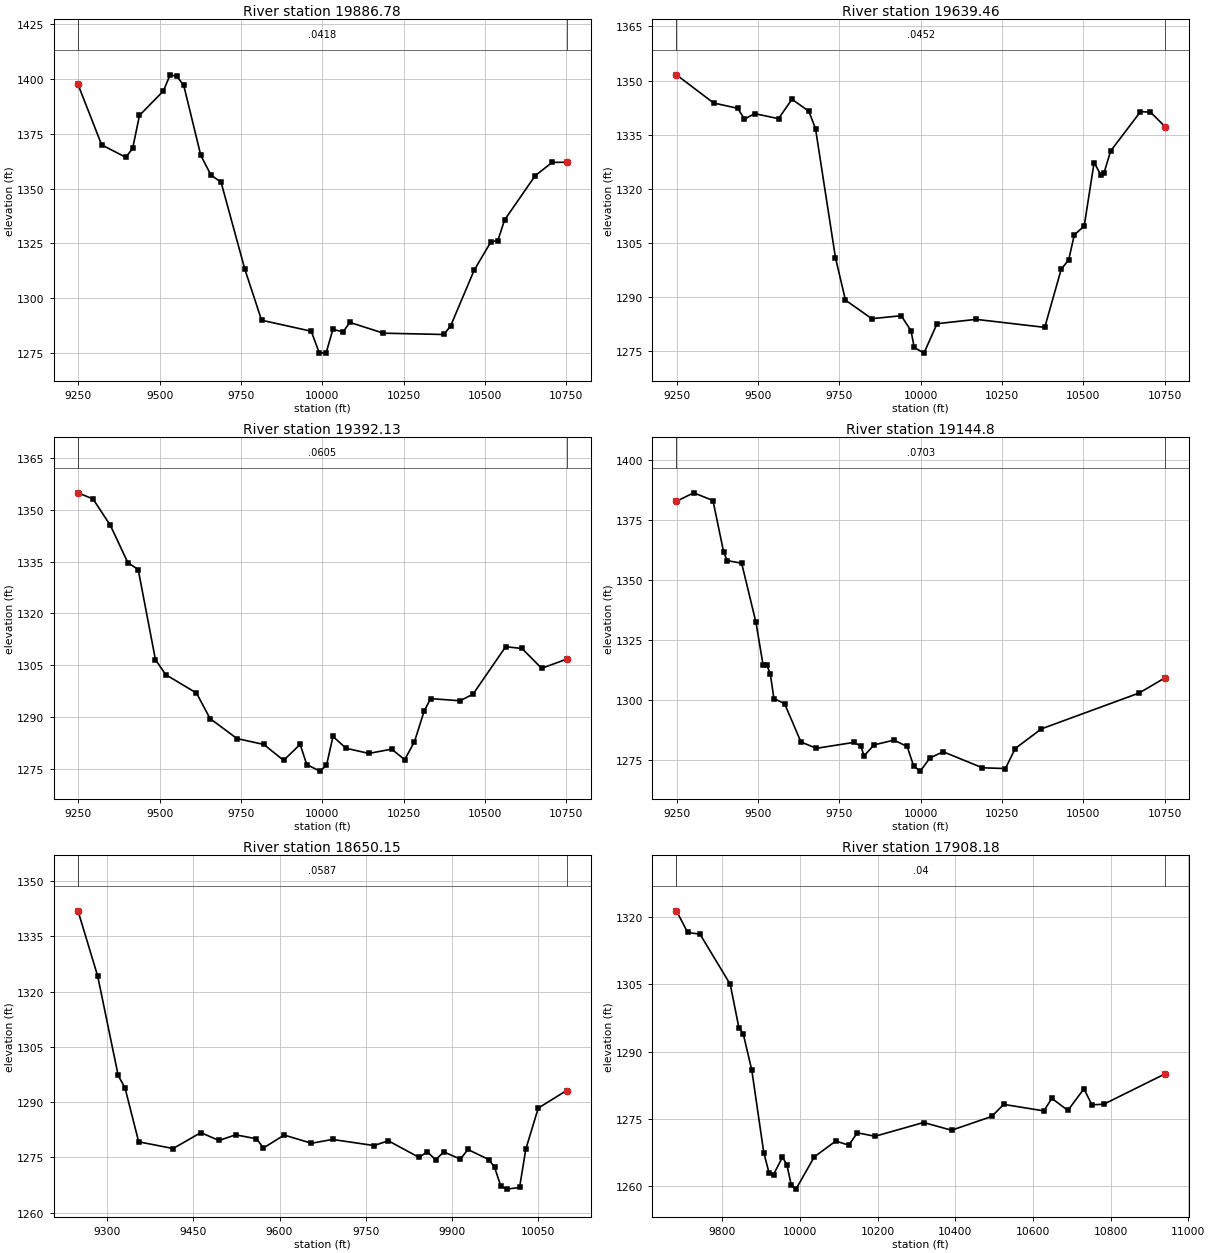
Type RM Length L Ch R = 1 ,19886.78,247.325100,247.325100,247.325100
XS GIS Cut Line= 6
772215.211775368763836.267416102772155.681571357764007.629816746
772096.655277239 764197.77188794771969.159991451764637.951734163
771870.547236722765021.588855852771792.785012646765276.998621938
#Sta/Elev= 30
9249.0321397.4659321.7941369.9169395.8981364.241 9417.071368.2579438.1581383.325
9511.4531394.3979532.3951401.7819553.336  1401.19574.2781396.9279626.6311365.105
9657.7971356.1639688.9371352.9099761.5971313.4919813.4971290.0649966.0921285.062
9990.6291275.28710011.661275.08910032.731285.89610063.981284.765 10084.8 1289.08
10187.941284.17110373.59 1283.57 10394.31287.368 10466.91312.804 10518.81325.838
10539.631326.25510560.471335.70210654.621355.86910706.991361.93810750.981361.971
#Mann= 3 , 0 , 0
9249.032  0.0418       09249.032  0.0418       010750.98  0.0418       0
#XS Ineff= 2 , 0
       0                               0
Bank Sta=9249.032,10750.98
Exp/Cntr=0.3,0.1

Type RM Length L Ch R = 1 ,19639.46,247.325100,247.325100,247.325100
XS GIS Cut Line= 6
771921.003327361 763787.16590926771826.039384695764072.552983652
771772.537218988764295.722282147 771754.48158027764435.285277789
771731.543502476764845.096029112771659.308140407765258.721139643
#Sta/Elev= 30
9249.0711351.6059363.3071343.8049437.2511342.3269458.1971339.3589489.6151340.857
9562.758 1339.469604.1191344.832 9655.821341.543  9676.51336.7059737.8661300.934
9768.5061289.193 9849.571284.0419939.9591284.8679969.9771280.7279979.984 1276.07
   10010  1274.510050.011282.65310170.121283.855 10381.21281.63710431.631297.679
10454.951300.404 10472.11307.26310502.491309.70210532.881327.29510553.231323.943
10563.411324.42310583.761330.50710675.541341.39710706.231341.26110750.961337.257
#Mann= 3 , 0 , 0
9249.071  0.0452       09249.071  0.0452       010750.96  0.0452       0
#XS Ineff= 2 , 0
       0                               0
Bank Sta=9249.071,10750.96
Exp/Cntr=0.3,0.1

Type RM Length L Ch R = 1 ,19392.13,247.325100,247.325100,247.325100
XS GIS Cut Line= 6
771709.163729925763791.659455913771589.490828429 764127.84278018
771517.691943441  764425.4451399771496.298467955 764590.53577259
771483.390946028764983.803234178771455.139138497765260.931305503
#Sta/Elev= 30
9249.0411354.863 9295.351353.0789348.774 1345.449402.1991334.6979434.2531332.666
9487.1791306.643 9518.761302.2969613.4091296.9849654.9951289.6159737.8271283.823
9819.9871282.1299881.264 1277.539932.0461282.1399952.2751276.3089992.734 1274.41
10012.971276.06910033.061284.42510073.241281.01410143.361279.532 10213.41280.763
10253.411277.72810283.411282.90510313.42 1291.8410333.421295.36910423.481294.747
10463.511296.653 10563.81310.37910613.961309.86310674.421304.13610750.961306.767
#Mann= 3 , 0 , 0
9249.041  0.0605       09249.041  0.0605       010750.96  0.0605       0
#XS Ineff= 2 , 0
       0                               0
Bank Sta=9249.041,10750.96
Exp/Cntr=0.3,0.1

Type RM Length L Ch R = 1 , 19144.8,494.650100,494.650100,494.650100
XS GIS Cut Line= 6
771527.224088783763733.191390309771345.124822026764138.965972994
771284.652822328764375.159433627 771267.63833347764523.802219164
771303.012541249764888.454226208771292.971443502765184.636361401
#Sta/Elev= 30
9249.0431382.798 9301.931386.3279361.2391383.124  9394.31361.491 9405.321358.052
9449.4011356.9839493.4821332.2649515.5221314.3549526.5431314.5879537.5631310.785
9548.5831300.5359581.409 1298.439631.7031282.4579678.8731279.7949794.8161282.276
9815.5561280.7449825.8141276.6699856.5861281.2329917.6631283.2159958.1571280.566
9978.3321272.3599998.5071270.28610028.771275.85210069.02 1278.35 10189.61271.675
 10260.21271.36710290.411279.71610370.751287.89810671.09 1302.8410750.911309.194
#Mann= 3 , 0 , 0
9249.043  0.0703       09249.043  0.0703       010750.91  0.0703       0
#XS Ineff= 2 , 0
       09861.177                       0
Bank Sta=9249.043,10750.91
Exp/Cntr=0.3,0.1

Type RM Length L Ch R = 1 ,18650.15,741.975300,741.975300,741.975300
XS GIS Cut Line= 6
771279.926788142763936.126309585770989.610908948764373.095294861
770953.671471273764416.040273158770888.772207327764478.805393193
770868.836091967764506.746306533770810.553555325764639.376959962
#Sta/Elev= 30
9249.2081341.923 9283.531324.203 9319.191297.2459331.0771293.874 9354.851279.247
9414.7091277.4279463.0971281.7459494.5261279.6089523.5821281.1489559.8731280.075
 9571.971277.5869608.1371281.0819655.5721278.861 9692.14 1279.899764.142 1278.24
 9789.381279.5199842.7441275.0239857.1291276.5549871.5131274.3859885.8981276.507
9914.6671274.5459927.7511277.1749964.2611274.4139974.3031272.2979985.1711267.134
9996.0391266.41210017.681266.879 10028.51277.24410050.161288.39310099.411293.159
#Mann= 3 , 0 , 0
9249.208  0.0587       09249.208  0.0587       010099.41  0.0587       0
#XS Ineff= 2 , 0
       09632.688                       0
Bank Sta=9249.208,10099.41
Exp/Cntr=0.3,0.1

Type RM Length L Ch R = 1 ,17908.18,451.005800,451.005800,451.005800
XS GIS Cut Line= 6
770838.830803842763598.516799976770802.910874831763682.588334821
770746.062106833763800.792270113770680.519797227763912.573907843
770604.016495703764065.798690046770421.684033751764777.306486338
#Sta/Elev= 30
9682.1991321.3679710.9991316.5499742.8541316.1659820.6851305.0019842.8781295.366
9853.9741294.0369876.1671285.8949907.0171267.5239920.9451262.9139932.318 1262.65
9955.0631266.5149966.4361264.8559978.0581260.2139989.9941259.39810037.141266.581
10092.491270.10410125.71 1269.1910148.031271.941 10193.51271.166 10318.51274.231
10390.761272.511   104941275.58510524.971278.264 10628.21276.81910648.841279.605
10690.141276.92410731.431281.73610752.071278.14610783.041278.32510940.27 1285.06
#Mann= 3 , 0 , 0
9682.199    0.04       09682.199    0.04       010940.27    0.04       0
#XS Ineff= 2 , 0
       0                10621.22       0
Bank Sta=9682.199,10940.27
Exp/Cntr=0.3,0.1

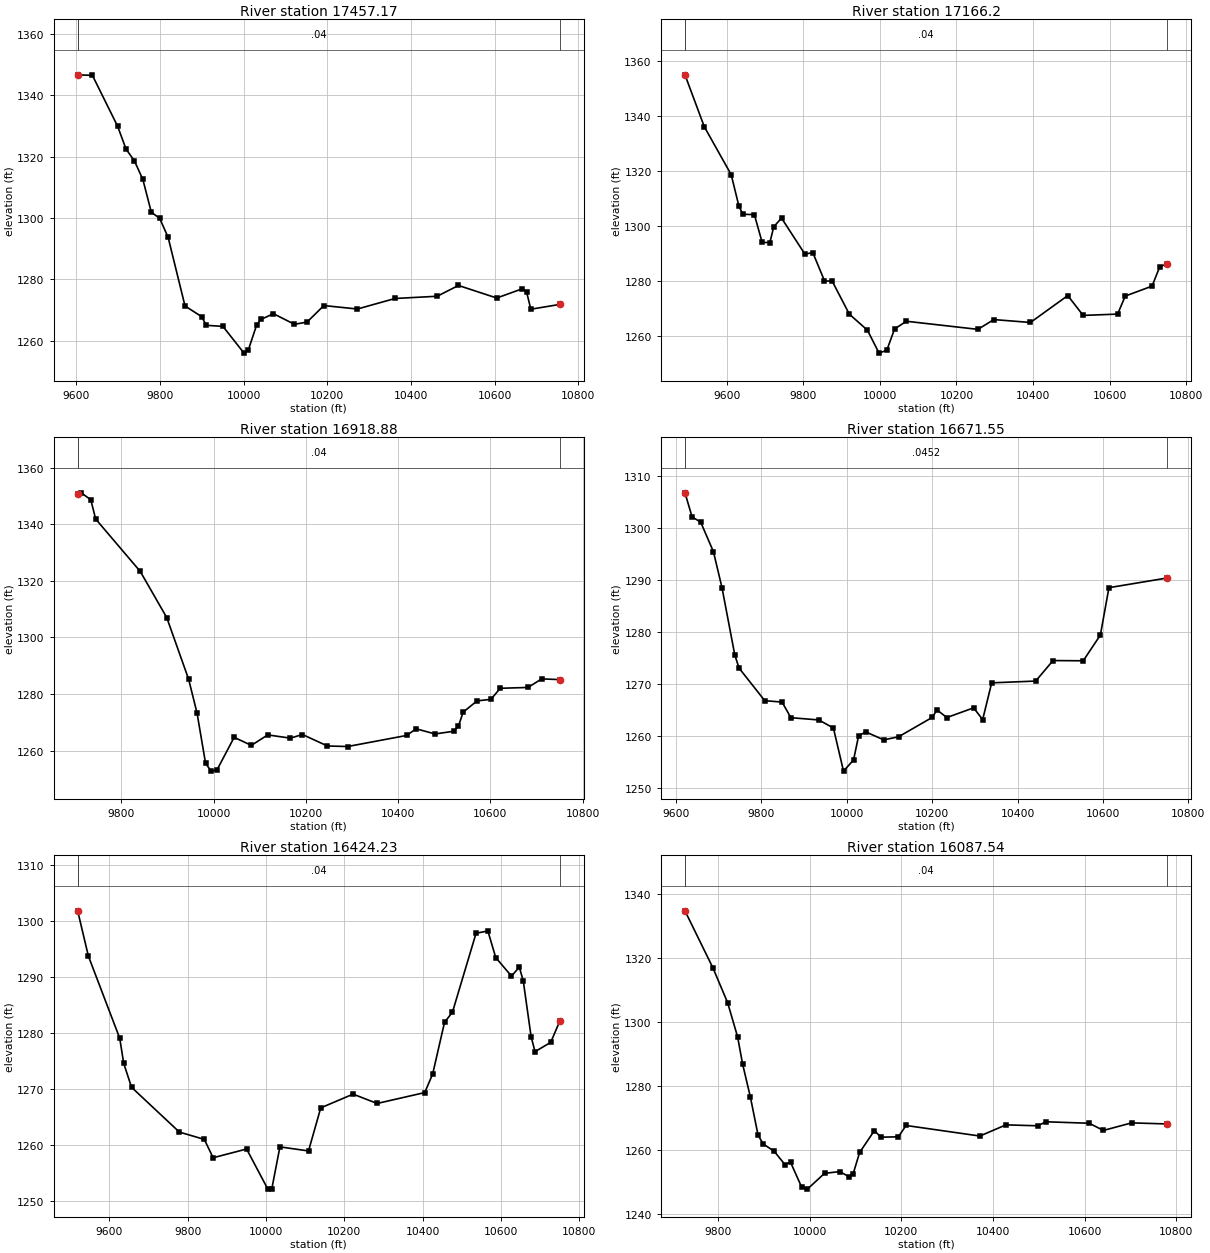
Type RM Length L Ch R = 1 ,17457.17,290.969500,290.969500,290.969500
XS GIS Cut Line= 6
770226.235746921763569.845814363770281.322913879764085.104074011
770289.635831949764241.834642321770285.505314654764331.961691022
770276.674298373764407.646919416770220.364168051764713.385448797
#Sta/Elev= 30
9603.4411346.747 9638.721346.5679698.9541329.9599719.0331322.5029739.1111318.648
9759.2531312.5829779.401 1301.919799.5481299.8699819.6951293.6649859.9891271.283
9900.2841267.7549910.3571264.9719950.652 1264.6210000.98 1255.8910011.031256.804
10031.131265.06810041.181266.87710071.331268.76310121.591265.29210151.671266.035
10191.791271.42110271.861270.29310361.95 1273.73 10462.71274.45910513.381277.983
10604.921273.88210666.021276.902 10676.21275.88810686.38 1270.2210756.021271.801
#Mann= 3 , 0 , 0
9603.441    0.04       09603.441    0.04       010756.02    0.04       0
#XS Ineff= 2 , 0
       0                10487.29       0
Bank Sta=9603.441,10756.02
Exp/Cntr=0.3,0.1

Type RM Length L Ch R = 1 , 17166.2,247.325100,247.325100,247.325100
XS GIS Cut Line= 6
769899.379101052763484.610708353769928.229099843    763730.97678
769986.121581655764028.236079971770083.199006974764414.463132154
770094.627426976764554.265493666770089.856446506764724.706556947
#Sta/Elev= 30
9490.3881354.9319540.8881336.0479611.2391318.5819631.3931307.1219641.5081304.188
9671.8531304.0299692.0831293.9369712.3131293.8769722.4281299.6169742.6971302.795
9803.9691289.6389824.3931290.2479855.0291279.9659875.4531279.7599919.9631267.818
9967.2621261.976 9997.651253.62910017.921254.68610038.221262.42310069.091265.232
10255.98 1262.2810297.591265.84110393.341264.78510490.841274.58210531.051267.358
 10621.11267.834 10641.11274.39610711.171278.02810731.191285.04210750.911286.198
#Mann= 3 , 0 , 0
9490.388    0.04       09490.388    0.04       010750.91    0.04       0
#XS Ineff= 2 , 0
       0                10346.98       0
Bank Sta=9490.388,10750.91
Exp/Cntr=0.3,0.1

Type RM Length L Ch R = 1 ,16918.88,247.325000,247.325000,247.325000
XS GIS Cut Line= 6
769635.496453653763847.430266677769694.827657097764002.450632841
769864.177387624764248.021283201 769935.31435174764391.764037888
769984.982298439 764581.80178046769998.637922517764804.464541822
#Sta/Elev= 30
9705.297 1350.599713.0661351.1389733.7811348.6959744.3141341.874 9840.981323.342
 9898.451307.0239945.8931285.2119964.1171273.2669982.6681255.4259994.9271252.721
10007.271253.11810044.561264.67310081.851261.83210117.421265.53210166.651264.382
10192.561265.67310246.891261.60610290.671261.42610418.361265.33410439.081267.692
10480.071265.869 10520.71266.82410530.831268.60810540.91 1273.5510571.161277.563
 10601.31278.10710621.371282.01910681.451282.30810711.451285.34610750.921285.082
#Mann= 3 , 0 , 0
9705.297    0.04       09705.297    0.04       010750.92    0.04       0
#XS Ineff= 2 , 0
       0                10323.69       0
Bank Sta=9705.297,10750.92
Exp/Cntr=0.3,0.1

Type RM Length L Ch R = 1 ,16671.55,247.325100,247.325100,247.325100
XS GIS Cut Line= 6
769495.682692156763898.261309614769513.099946301764147.801165244
769678.890952463764451.589817666769738.595494675764632.126127825
769761.060084629764758.372390441769774.768614553764971.476757537
#Sta/Elev= 30
9620.8951306.6919637.6341302.0419657.6341301.0739687.6371295.354 9707.641288.452
9737.6451275.4939747.6471272.974 9807.831266.7099848.4681266.4419868.9891263.437
 9934.451263.0029968.6961261.448 9992.361253.15810015.911255.31810027.721259.952
10044.481260.70210086.721259.16910121.391259.76610200.261263.49410211.32 1264.93
10234.541263.46610297.231265.33210318.371263.06910339.521270.14110442.631270.482
10483.211274.42610553.971274.38310594.151279.32910614.241288.44510750.911290.313
#Mann= 3 , 0 , 0
9620.895  0.0452       09620.895  0.0452       010750.91  0.0452       0
#XS Ineff= 2 , 0
       0                10252.59       0
Bank Sta=9620.895,10750.91
Exp/Cntr=0.3,0.1

Type RM Length L Ch R = 1 ,16424.23,336.689800,336.689800,336.689800
XS GIS Cut Line= 6
769477.260310286763897.711387765769443.497086501764158.986884066
769409.564890216764241.341683391769349.878225455764331.230395025
769274.841532333 764623.43326537769219.012546284765088.533688812
#Sta/Elev= 30
9518.6721301.7869546.0111293.7159626.2611279.0059636.3061274.5499656.396 1270.27
9778.5381262.2739842.3131260.9639864.7531257.6889950.3631259.24710004.531252.083
10014.721252.14210035.441259.62910108.511258.90310139.761266.59710222.381269.048
 10283.81267.382 10405.51269.32710425.731272.65310456.06 1281.8910476.181283.668
10536.551297.77810566.731298.19710586.85 1293.4410627.031290.13310647.091291.722
10657.121289.29610677.181279.33810687.211276.63310727.341278.29710750.951282.163
#Mann= 3 , 0 , 0
9518.672    0.04       09518.672    0.04       010750.95    0.04       0
#XS Ineff= 2 , 0
       0                               0
Bank Sta=9518.672,10750.95
Exp/Cntr=0.3,0.1

Type RM Length L Ch R = 1 ,16087.54,356.980900,356.980900,356.980900
XS GIS Cut Line= 6
769293.598289835763856.334924658769208.754102478764052.209700924
769004.159754824764289.986706958768928.009788646764405.432697395
768859.581539712764570.712411209768814.607949269764771.470122983
#Sta/Elev= 30
9728.0311334.789 9789.191316.9259821.1351306.0959842.8831295.4259853.823 1286.91
  9870.71276.6719887.5471264.7099898.875 1261.959922.3191259.7579946.0571255.557
9958.3271256.2889982.8671248.4099995.1371247.87210032.481252.79910065.831253.355
10085.261251.78610094.861252.59210109.121259.31410141.371266.166 10155.41264.096
10193.551264.20710210.521267.74810371.511264.453 10428.31267.94210498.191267.648
10515.411268.90610609.981268.44410641.031266.20210702.551268.56110780.371268.227
#Mann= 3 , 0 , 0
9728.031    0.04       09728.031    0.04       010780.37    0.04       0
#XS Ineff= 2 , 0
       0                               0
Bank Sta=9728.031,10780.37
Exp/Cntr=0.3,0.1

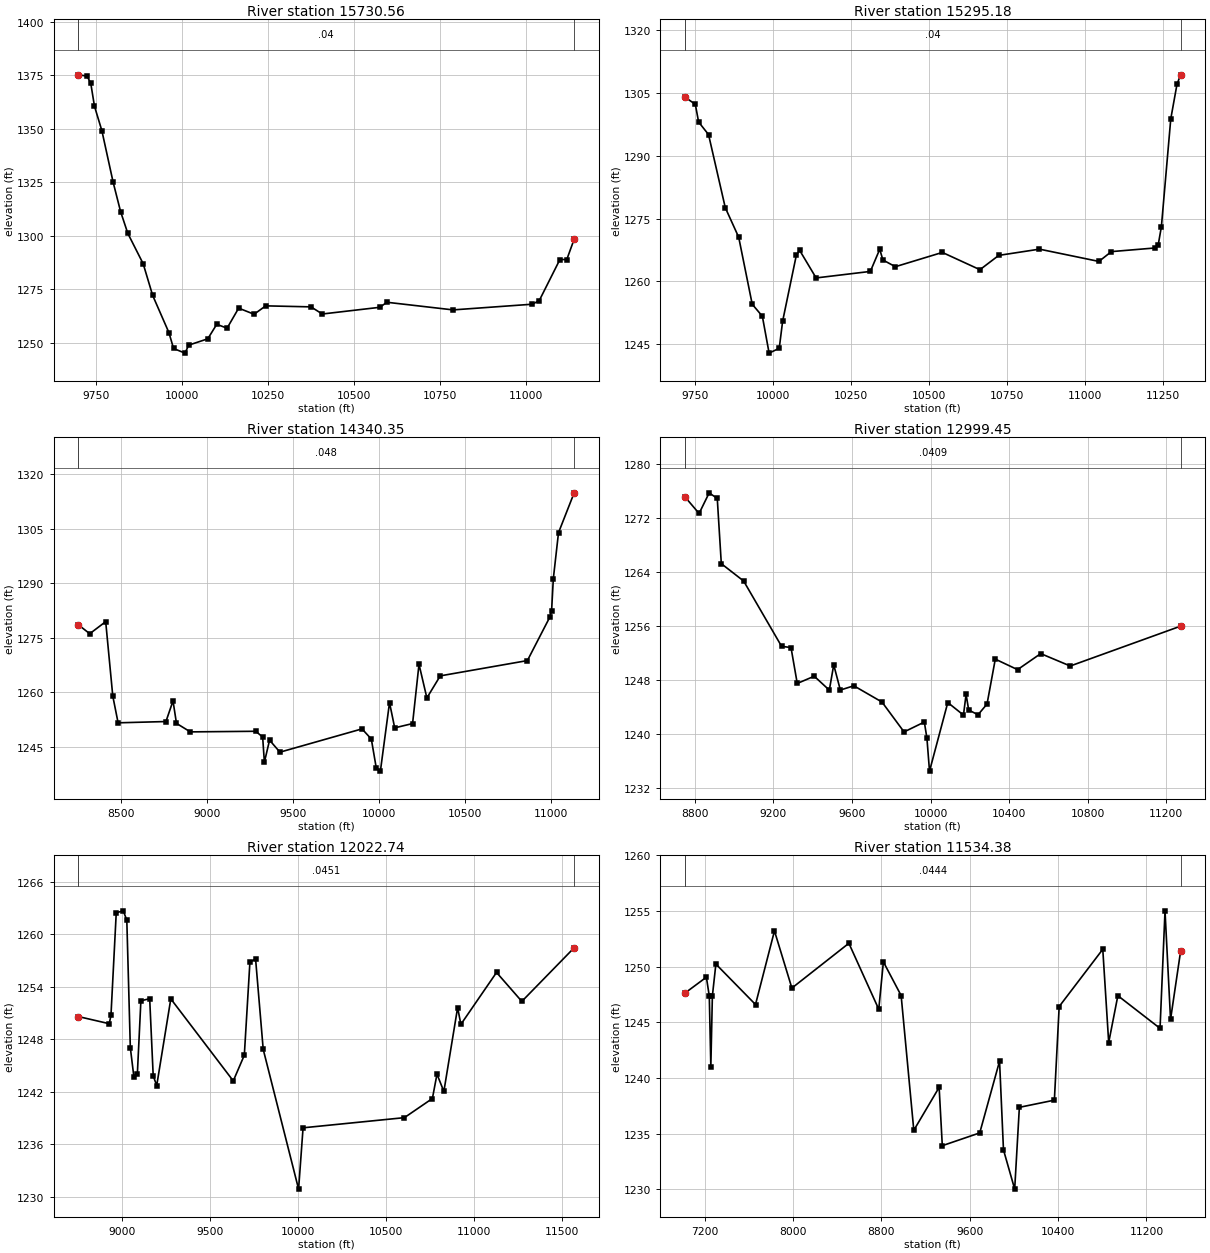
Type RM Length L Ch R = 1 ,15730.56,435.382800,435.382800,435.382800
XS GIS Cut Line= 6
  768979.7733689763661.240934427768833.767279203 763991.37265058
768714.209568167 764229.41655209768651.722824172764397.059012798
768602.616178273764649.004429093768581.456639489765026.451055319
#Sta/Elev= 30
9697.4511375.2639722.8211374.6939733.5951371.3039744.3691360.6099765.9161349.153
 9798.431325.2519820.2951311.3849841.3191301.2079886.0271287.0059913.5441272.239
9960.766 1254.889974.3391247.44710007.461245.271 10018.51249.00810073.851251.964
10099.87 1258.7310129.971256.92410163.651266.28610208.541263.43210242.221267.352
10373.971266.87810406.711263.54510574.081266.676 10594.71269.02710787.081265.464
11017.651268.12311037.671269.81611097.681288.99711117.691288.98311139.141298.485
#Mann= 3 , 0 , 0
9697.451    0.04       09697.451    0.04       011139.14    0.04       0
#XS Ineff= 2 , 0
       0                               0
Bank Sta=9697.451,11139.14
Exp/Cntr=0.3,0.1

Type RM Length L Ch R = 1 ,15295.18,954.824500,954.824500,954.824500
XS GIS Cut Line= 6
768558.199941995763513.120541198768412.789007304763882.887410549
768377.439459968764023.768157224768374.291226011764181.548206578
768413.158940999 764651.96353921768433.431453287765066.527136905
#Sta/Elev= 30
9717.1941304.0499750.8881302.2799761.4571298.0699793.2581295.061 9846.851277.612
9889.8281270.5569933.1151254.5599965.5811251.6839987.225 1242.8810019.691244.041
10030.54 1250.5110074.311266.22210084.971267.43310137.781260.83510311.51 1262.39
10341.561267.68310351.56 1265.1310391.571263.51710542.041266.92610662.491262.803
10722.721266.21710853.091267.70811043.441264.776 11083.5 1267.1211223.631267.993
11233.631268.80911243.641273.08311273.671298.82711293.691307.11311305.221309.333
#Mann= 3 , 0 , 0
9717.194    0.04       09717.194    0.04       011305.22    0.04       0
#XS Ineff= 2 , 0
       0                               0
Bank Sta=9717.194,11305.22
Exp/Cntr=0.3,0.1

Type RM Length L Ch R = 1 ,14340.35,1340.902500,1340.902500,1340.902500
XS GIS Cut Line= 6
767719.760956854762630.612271443767587.860236555763159.318212375
767577.626257509763805.056898415767658.533272058764022.491951615
768084.349879265764551.527839363768228.322397649765305.795056537
#Sta/Elev= 30
8253.1391278.595  8319.51276.1368412.2591279.4558453.4851259.0018484.4041251.638
 8762.681251.989 8803.771257.6748823.9051251.4878904.4431249.1459285.0491249.311
9325.1251247.7249335.1441240.8069365.2431246.8689425.6631243.5689902.8891249.971
9957.0871247.1759986.0181239.17710009.841238.35410062.891257.19410093.031250.252
   101971251.43510234.381267.73910280.16 1258.48   103581264.54810864.761268.752
10995.471280.73411005.521282.46911015.571291.27511045.681303.91411136.731314.877
#Mann= 3 , 0 , 0
8253.139   0.048       08253.139   0.048       011136.73   0.048       0
#XS Ineff= 2 , 0
       09799.891        10071.88       0
Bank Sta=8253.139,11136.73
Exp/Cntr=0.3,0.1

Type RM Length L Ch R = 1 ,12999.45,976.710100,976.710100,976.710100
XS GIS Cut Line= 6
767572.704582283762594.179271595767455.147778593763040.628094084
767324.591453758763354.062594281          766885763951.619417086
766945.673932791764194.666272998767393.590599447764767.582939684
#Sta/Elev= 30
8749.0581275.1018821.8361272.6258873.2171275.6778914.3231274.8398934.8751265.195
9048.6381262.6259241.6831252.963 9289.641252.7839321.4131247.4719407.8411248.541
 9484.68 1246.489507.0891250.2259540.7011246.4969609.4911247.1249752.7871244.719
9865.0551240.2979968.333 1241.769981.4721239.3629994.6111234.49710087.641244.648
10167.441242.79310180.741245.85410194.04 1243.5410241.551242.83910287.431244.428
10329.421251.069 10442.81249.51410560.671251.88610710.961250.05211272.75 1255.95
#Mann= 3 , 0 , 0
8749.058  0.0409       08749.058  0.0409       011272.75  0.0409       0
#XS Ineff= 2 , 0
       09795.046        10312.68       0
Bank Sta=8749.058,11272.75
Exp/Cntr=0.3,0.1

Type RM Length L Ch R = 1 ,12022.74,488.355000,488.355000,488.355000
XS GIS Cut Line= 6
766136.388934713762249.727415103766134.974634913762863.837739999
766213.790614581763220.469779619766418.275192262763628.752775667
766570.673932791764116.541272998767127.965599447764783.207939669
#Sta/Elev= 30
8749.0681250.5968924.545 1249.78 8934.551250.7268964.5661262.4539004.5871262.672
9024.5981261.598  9044.61247.0449064.6011243.7399084.6031244.0649104.6041252.392
9154.6081252.636 9174.611243.8259194.6121242.7189274.6841252.6179629.7161243.244
9692.5131246.1839724.2431256.7839756.4561257.1949799.8781246.852   100011230.884
10026.421237.88810602.271239.04810761.541241.235 10787.61244.015 10826.71242.039
10904.911251.61610923.411249.704 11126.11255.63311269.851252.32711567.291258.452
#Mann= 3 , 0 , 0
8749.068  0.0451       08749.068  0.0451       011567.29  0.0451       0
#XS Ineff= 2 , 0
       09778.188        10382.55       0
Bank Sta=8749.068,11567.29
Exp/Cntr=0.3,0.1

Type RM Length L Ch R = 1 ,11534.38,283.845700,283.845700,283.845700
XS GIS Cut Line= 4
 763836.01360515761588.714509298765656.737901927763360.292346414
766023.404568582763745.709013061766877.230653674764877.878212619
#Sta/Elev= 30
7019.6141247.6217215.042 1249.067241.4411247.3637255.3931241.0337269.3461247.372
 7301.081250.2377660.0181246.6047831.6471253.2177989.3831248.082 8505.611252.105
8776.2241246.1778818.0811250.4368978.818 1247.419093.5351235.3079322.9691239.165
9351.6491233.9259690.7121235.0739870.1441241.5159905.6691233.55110007.231230.023
10049.58 1237.3710366.621238.01510410.161246.425   108051251.56610858.58 1243.19
10941.621247.399 11323.61244.46311368.62 1255.0211418.721245.262   115101251.404
#Mann= 3 , 0 , 0
7019.614  0.0444       07019.614  0.0444       0   11510  0.0444       0
#XS Ineff= 2 , 0
       09798.936        10157.84       0
Bank Sta=7019.614,11510
Exp/Cntr=0.3,0.1

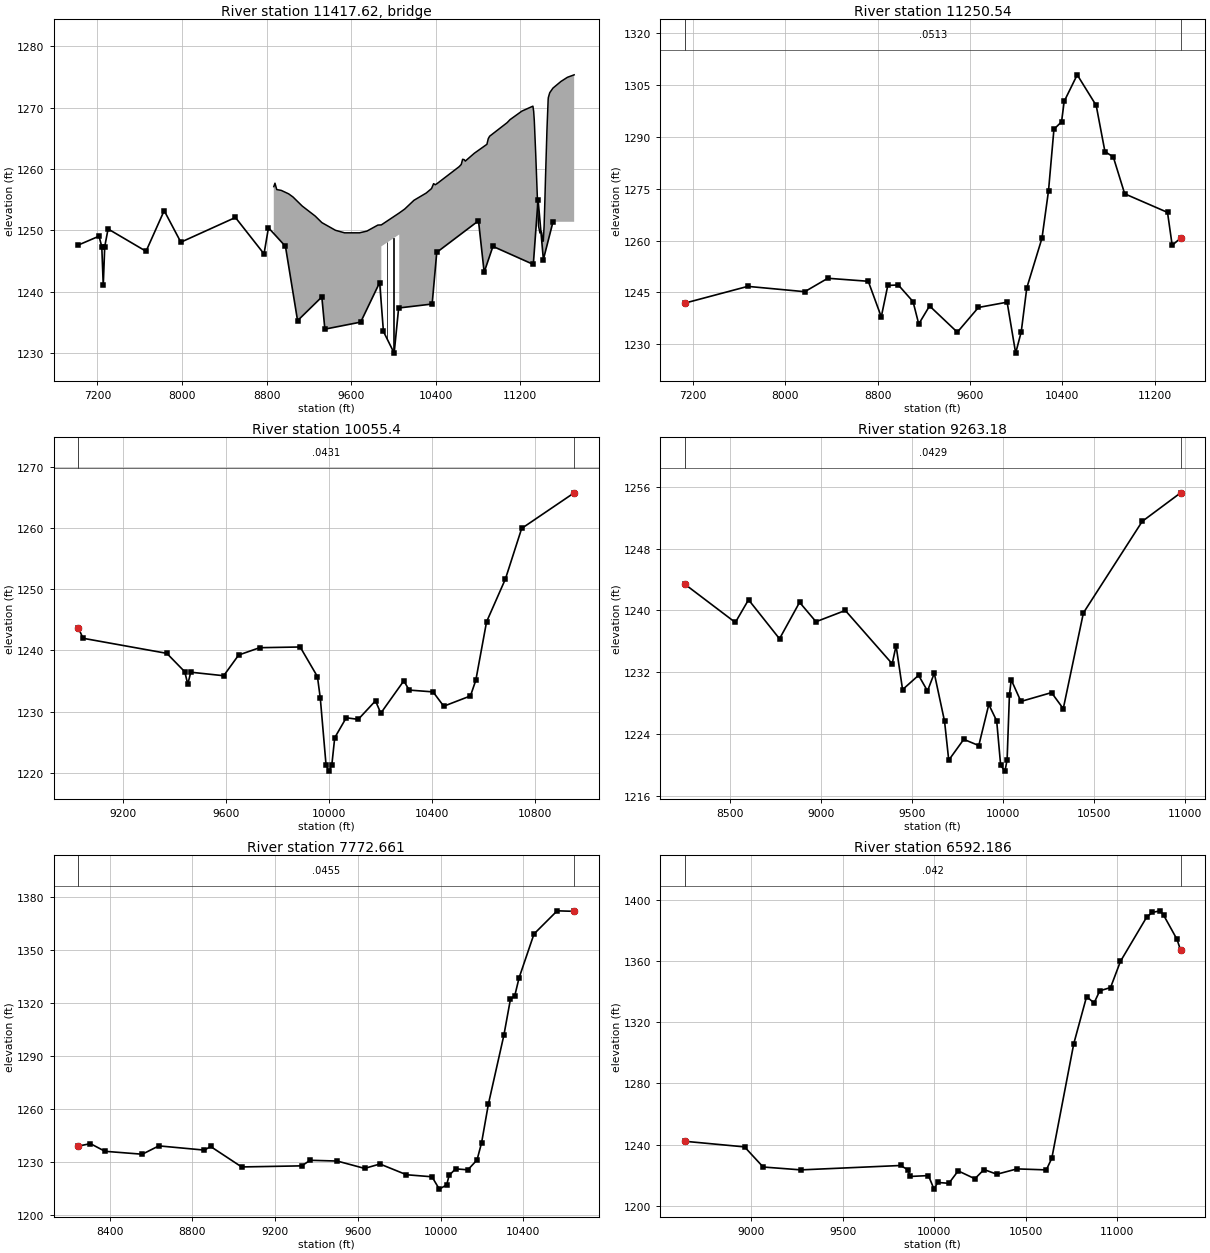
Type RM Length L Ch R = 3 ,11417.62,,,
BEGIN DESCRIPTION:
END DESCRIPTION:
Bridge Culvert--1,0,-1,-1, 0
Deck Dist Width WeirC Skew NumUp NumDn MinLoCord MaxHiCord MaxSubmerge Is_Ogee
118.464900,46.915900,2.6,0, 60, 60, , , 0.95, 0, 0,0,,
 8868.68 8879.81 8896.67 8938.61 9008.60 9050.45 9137.39 9260.15 9323.42 9452.21
 9538.07 9679.54 9749.44 9852.90 9885.92 9885.9210055.2110055.2110106.9310194.86
10309.8210348.1410360.9110380.1710396.2410412.0010621.2710641.9210654.6910669.48
10680.2410765.9210884.6110897.3910910.5811076.2111103.4511215.9711319.7311326.83
11333.0011346.2611359.5311372.8011386.0711399.3411402.9011412.6011418.1211425.87
11433.3411439.1411452.4111463.7711465.6811478.9811509.4111585.4911646.3611709.95
 1257.13 1257.69 1256.65 1256.52 1255.96 1255.44 1253.97 1252.34 1251.27 1250.02
 1249.61 1249.61 1249.89 1250.87 1250.90 1250.90 1252.84 1252.84 1253.48 1254.91
 1256.08 1256.63 1256.82 1257.61 1257.44 1257.61 1260.37 1260.74 1261.58 1261.52
 1261.29 1262.57 1264.02 1264.94 1265.34 1267.55 1268.04 1269.43 1270.23 1269.41
 1267.85 1262.47 1256.44 1250.72 1249.58 1249.82 1249.58 1248.22 1248.29 1250.80
 1255.10 1258.73 1266.28 1271.27 1271.63 1272.42 1273.17 1274.26 1274.93 1275.33
  257.13  257.69  256.65  256.52  255.96  255.44  253.97  252.34  251.27  250.02
  249.61  249.61  249.89  250.87  250.90 1247.40 1249.34  252.84  253.48  254.91
  256.08  256.63  256.82  257.61  257.44  257.61  260.37  260.74  261.58  261.52
  261.29  262.57  264.02  264.94  265.34  267.55  268.04  269.43  270.23  269.41
  267.85  262.47  256.44  250.72  249.58  249.82  249.58  248.22  248.29  250.80
  255.10  258.73  266.28  271.27  271.63  272.42  273.17  274.26  274.93  275.33
 8868.68 8879.81 8896.67 8938.61 9008.60 9050.45 9137.39 9260.15 9323.42 9423.59
 9469.84 9538.07 9679.54 9749.44 9838.59 9894.39 9916.25 9916.2510085.5410085.54
10194.8610309.8210360.9110380.1710396.2410412.0010621.2710641.9210654.6910669.48
10680.2410765.9210884.6110897.3910910.5811076.2111103.4511215.9711319.7311326.83
11333.0011346.2611359.5311372.8011386.0711399.3411402.9011412.6011418.1211425.87
11433.3411439.1411452.4111463.7711465.6811478.9811509.4111585.4911646.3611709.95
 1257.13 1257.69 1256.65 1256.52 1255.96 1255.44 1253.97 1252.34 1251.27 1250.23
 1249.92 1249.61 1249.61 1249.89 1250.77 1250.93 1251.19 1251.19 1253.19 1253.19
 1254.91 1256.08 1256.82 1257.61 1257.44 1257.61 1260.37 1260.74 1261.58 1261.52
 1261.29 1262.57 1264.02 1264.94 1265.34 1267.55 1268.04 1269.43 1270.23 1269.41
 1267.85 1262.47 1256.44 1250.72 1249.58 1249.82 1249.58 1248.22 1248.29 1250.80
 1255.10 1258.73 1266.28 1271.27 1271.63 1272.42 1273.17 1274.26 1274.93 1275.33
  257.13  257.69  256.65  256.52  255.96  255.44  253.97  252.34  251.27  250.23
  249.92  249.61  249.61  249.89  250.77  250.93  251.19 1247.69 1249.69  253.19
  254.91  256.08  256.82  257.61  257.44  257.61  260.37  260.74  261.58  261.52
  261.29  262.57  264.02  264.94  265.34  267.55  268.04  269.43  270.23  269.41
  267.85  262.47  256.44  250.72  249.58  249.82  249.58  248.22  248.29  250.80
  255.10  258.73  266.28  271.27  271.63  272.42  273.17  274.26  274.93  275.33
Pier Skew, UpSta & Num, DnSta & Num=  ,9941.68, 2 ,9972.01, 2 , 0 , 0 , 0 ,,
    4.00    4.00
  251.49 1251.49
    4.00    4.00
  251.85 1251.85
Pier Skew, UpSta & Num, DnSta & Num=  ,9999.44, 2 ,10029.77, 2 , 0 , 0 , 0 ,,
    4.00    4.00
  252.18 1252.18
    4.00    4.00
  252.53 1252.53
BR Coef=-1 , 0 , 0 ,, 0 ,,,0.8,0,1,0,
WSPro=,,,, 1 ,,,, 0 ,,,, 0 ,,,,-1 ,-1 ,-1 , 0 , 0 , 0 , 0 , 0
BC Design=,, 0 ,, 0 ,,,,,,

Type RM Length L Ch R = 1 ,11250.54,1195.132900,1195.132900,1195.132900
XS GIS Cut Line= 6
763702.641209215761798.284821793 765445.53859973763566.312346518
 765688.59519586763776.452168584765839.461980313764000.784517646
765935.679670423764184.104537755766549.480957508764985.049290866
#Sta/Elev= 30
7130.958  1241.97676.0171246.7498169.327 1245.218368.8511249.0948719.0151248.223
8831.7721237.928 8888.151247.0178979.0291247.1579106.7411242.3369155.9471235.855
9249.7541241.0859489.8761233.4899672.4761240.6469921.1331242.1769994.9531227.434
10043.161233.58810091.281246.30810222.85 1260.7110279.311274.392 10326.3 1292.21
10392.251294.36710414.961300.27310527.791307.95810692.131299.09110767.721285.756
10840.151284.18610938.791273.53211309.471268.15411349.791258.63511422.921260.713
#Mann= 3 , 0 , 0
7130.958  0.0513       07130.958  0.0513       011422.92  0.0513       0
#XS Ineff= 2 , 0
       09803.825        10184.46       0
Bank Sta=7130.958,11422.92
Exp/Cntr=0.3,0.1

Type RM Length L Ch R = 1 , 10055.4,792.225000,792.225000,792.225000
XS GIS Cut Line= 6
764302.732093871762609.345904052          764675763237.152331784
764915.662414546763717.886736019764970.844268136763929.350769694
765007.478741049764054.379973758765104.647560889 764348.35710485
#Sta/Elev= 30
9027.2541243.6789045.4541241.9749370.9781239.5089440.7331236.4969452.3591234.459
9463.9851236.4269591.8691235.8519649.9991239.233 9731.381240.4329888.9241240.549
9956.0231235.7069967.206 1232.159989.5721221.20710000.751220.25610011.941221.264
10023.12 1225.7110067.851228.97510114.55 1228.7210181.571231.74910202.051229.723
10291.521235.01710312.351233.50610405.171233.20810446.621230.86810550.46 1232.55
 10571.3 1235.1310612.981244.66110686.281251.67410749.33 1259.9310953.231265.749
#Mann= 3 , 0 , 0
9027.254  0.0431       09027.254  0.0431       010953.23  0.0431       0
#XS Ineff= 2 , 0
       09838.673                       0
Bank Sta=9027.254,10953.23
Exp/Cntr=0.3,0.1

Type RM Length L Ch R = 1 , 9263.18,1490.518300,1490.518300,1490.518300
XS GIS Cut Line= 6
763973.716061493762255.162658947 764045.36568195763094.324656185
764126.703767847763420.147414334764237.347954653763596.789880809
764766.851208657764156.879041966 765043.63232865764648.621781593
#Sta/Elev= 30
8249.159  1243.4 8527.371238.4558600.0251241.3888770.5251236.3468880.9241241.056
8971.3261238.5499132.6371240.0069390.6851233.1169412.0871235.4489447.894 1229.78
 9535.971231.6319585.0171229.6049622.4031231.8959678.9821225.6839701.9821220.663
9784.6261223.3569867.3131222.5529922.4371227.8599965.8641225.7479987.8441219.998
10011.46 1219.2510023.251220.71210035.981229.04610045.861231.04610099.371228.252
10267.651229.39310332.371227.31810443.231239.69110767.111251.51510978.361255.201
#Mann= 3 , 0 , 0
8249.159  0.0429       08249.159  0.0429       010978.36  0.0429       0
#XS Ineff= 2 , 0
       09649.593                       0
Bank Sta=8249.159,10978.36
Exp/Cntr=0.3,0.1

Type RM Length L Ch R = 1 ,7772.661,1180.475700,1180.475700,1180.475700
XS GIS Cut Line= 6
763885.090633678762476.579774646763914.686952265763258.897515082
763871.175543648763784.466834309763823.115341961763943.191757317
763562.611962716764380.802026656763467.841820574764776.351377163
#Sta/Elev= 30
8249.1441238.9028307.6841240.2828377.8271235.9518558.0991234.2918638.189 1239.02
8858.3031236.6218888.3131238.6759038.3171227.0859328.8091227.7059369.0131230.854
9499.9811230.4329632.1761226.2659706.6731228.7519834.8461222.6689957.9881221.517
 9993.551214.52210029.04 1216.9410040.641222.24910071.791226.004 10131.41225.459
10175.731231.06110197.67 1240.7710230.591262.67510305.39 1301.67 10337.11322.057
10358.03 1324.0510378.891334.19410451.021359.06310562.931372.15810645.041371.878
#Mann= 3 , 0 , 0
8249.144  0.0455       08249.144  0.0455       010645.04  0.0455       0
#XS Ineff= 2 , 0
       09498.439                       0
Bank Sta=8249.144,10645.04
Exp/Cntr=0.3,0.1

Type RM Length L Ch R = 1 ,6592.186,1303.721700,1303.721700,1303.721700
XS GIS Cut Line= 4
763410.862052679762183.181401625763146.493024826          763745
763156.042040914764362.331847042763274.665149868764854.398076653
#Sta/Elev= 30
8638.3431242.1428964.7391238.4539066.1621225.2789272.6431223.4019816.6881226.275
9857.2571223.4239867.3991219.0889968.8221219.6639999.2491210.79510019.53 1215.17
10080.391214.608 10131.11222.74510222.381217.59910272.381223.62110342.391220.546
10452.411224.04810612.421223.39310642.431230.99310762.441306.05510832.451336.915
10873.391332.72210904.251340.67910963.351342.829 11017.41359.99711161.411389.107
11192.27 1392.0311233.411393.07811253.991390.03211325.991374.43611345.951367.248
#Mann= 3 , 0 , 0
8638.343   0.042       08638.343   0.042       011345.95   0.042       0
#XS Ineff= 2 , 0
       09673.072                       0
Bank Sta=8638.343,11345.95
Exp/Cntr=0.3,0.1