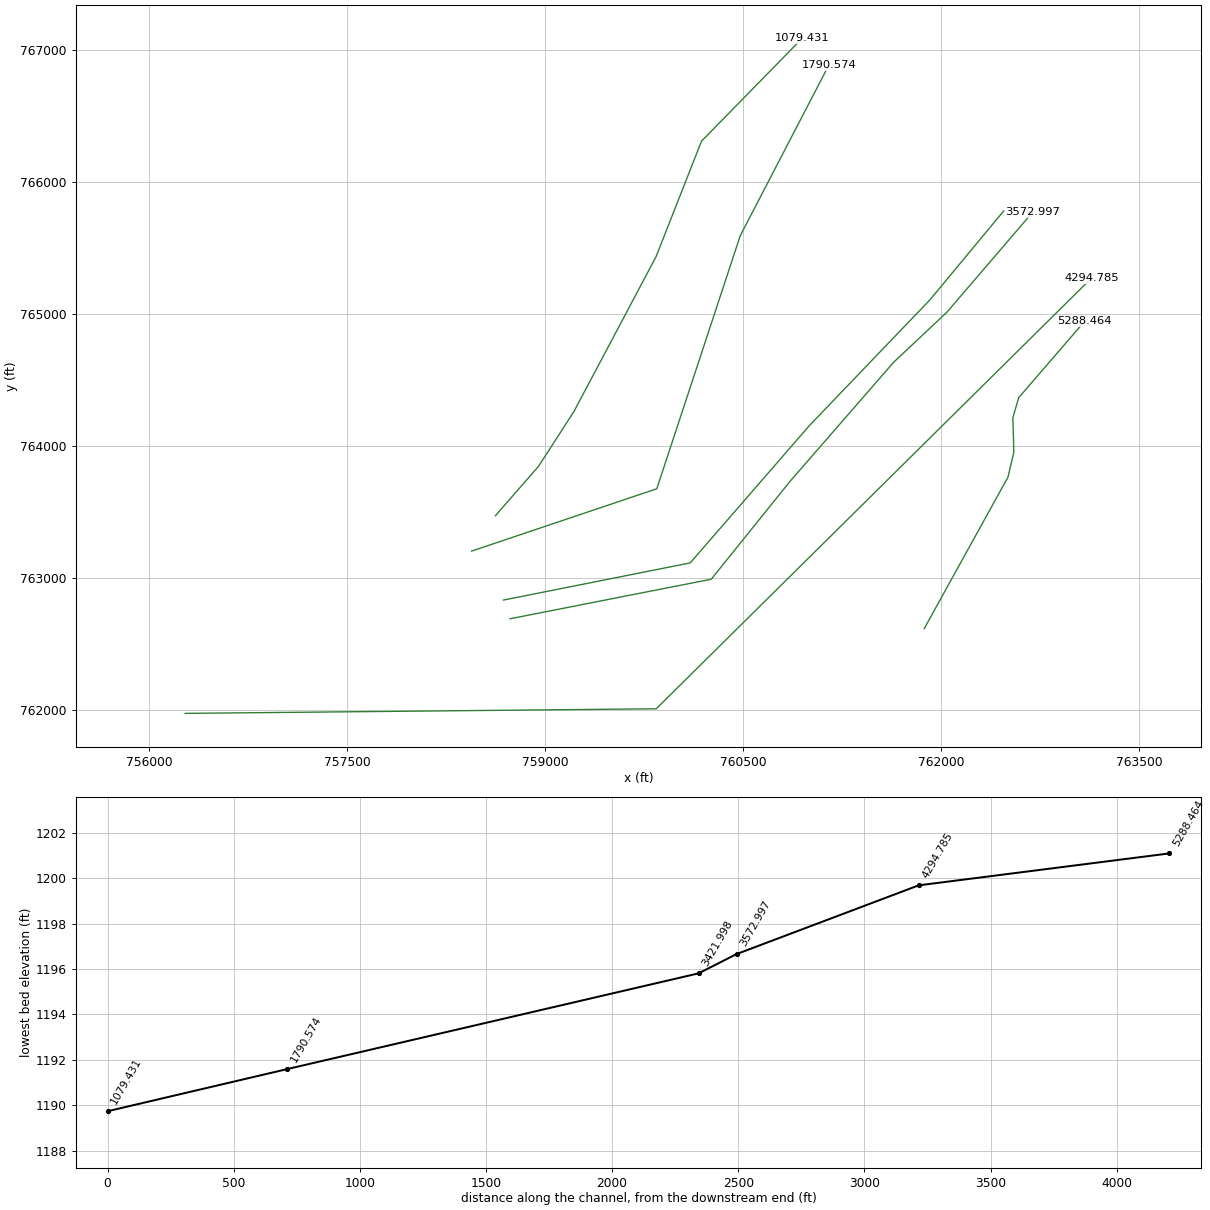
HEC-RAS study 14213_ras.prj: 14213

--- 14213_ras.g01 (geometry) --- (continued)

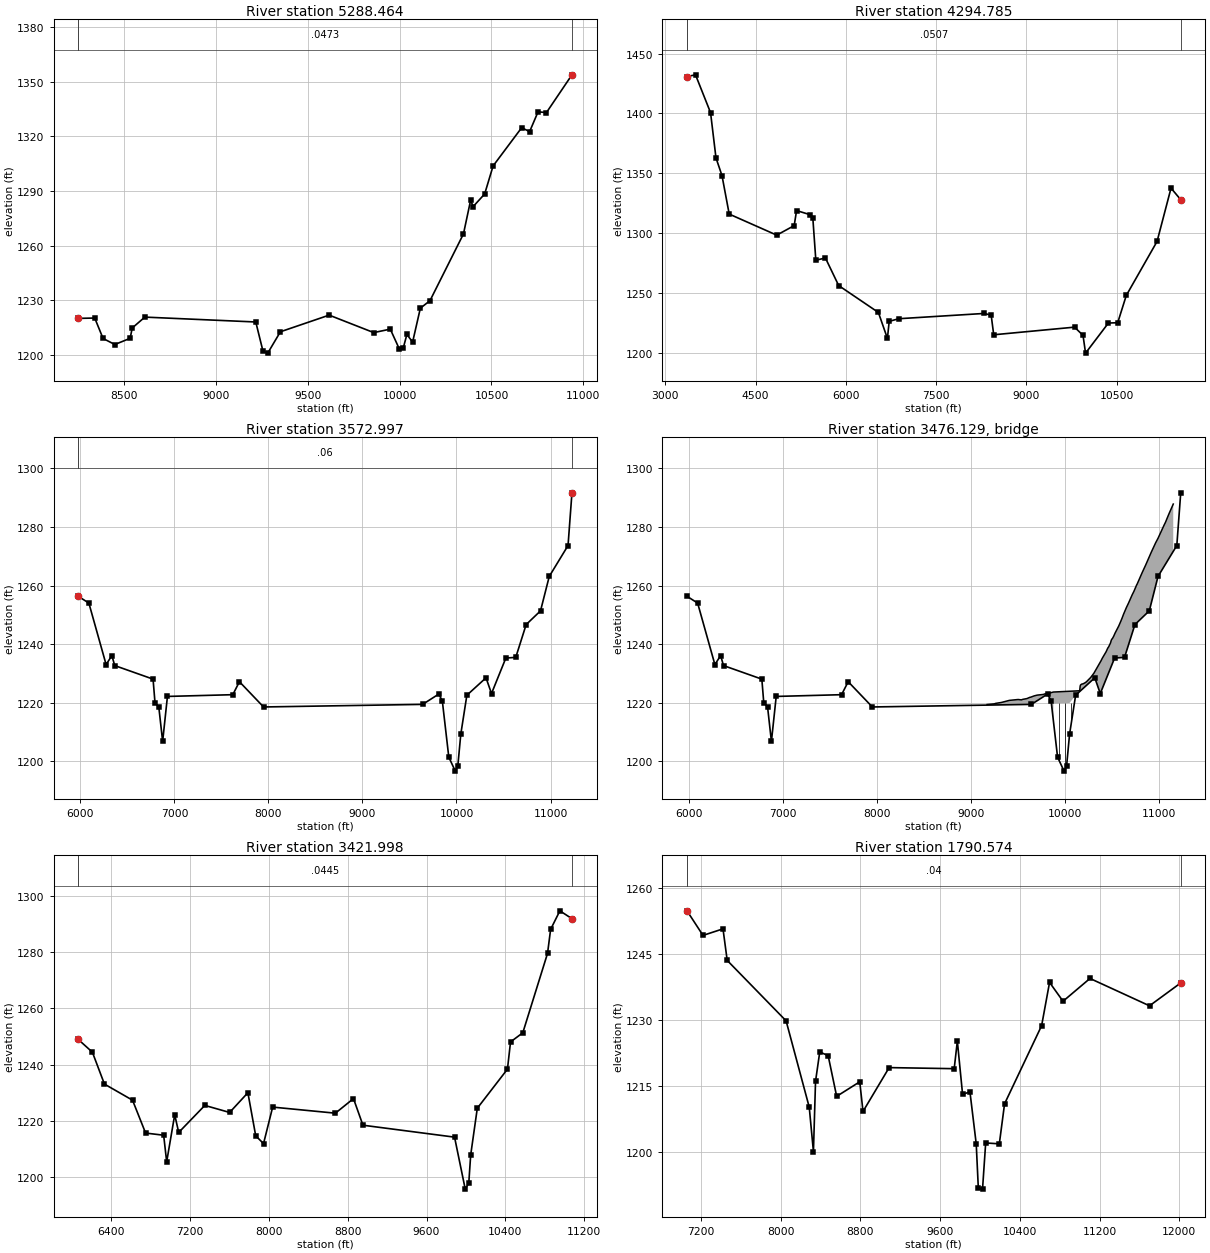
Type RM Length L Ch R = 1 ,5288.464,993.678900,993.678900,993.678900
XS GIS Cut Line= 6
761871.496132628762615.576206646762505.893635231763763.173116653
762550.275056302763952.144064239762542.699741528 764212.60265154
762587.259392768764365.000000015763085.746865243764942.267046228
#Sta/Elev= 30
8249.0921220.1588339.0281220.3458384.3221209.1428448.3971205.834 8531.841209.221
8543.2651214.8928611.8151220.858  9216.21218.182 9255.751202.0629281.3911201.103
9350.2561212.8129615.9631221.9429858.797 1212.369948.931 1214.26    99991203.178
10019.051203.69710039.251211.32610070.561207.17710112.641225.74710165.231229.883
10347.511266.482 10386.51284.95210400.36 1281.47   104631288.38610508.911303.762
10664.611324.73210707.811322.55910753.711333.42410799.621333.03510938.461353.719
#Mann= 3 , 0 , 0
8249.092  0.0473       08249.092  0.0473       010938.46  0.0473       0
#XS Ineff= 2 , 0
       09630.316                       0
Bank Sta=8249.092,10938.46
Exp/Cntr=0.3,0.1

Type RM Length L Ch R = 1 ,4294.785,721.788200,721.788200,721.788200
XS GIS Cut Line= 3
756273.392697304 761973.11929749759841.101030648762007.841519728
763139.712141722765271.730408609
#Sta/Elev= 30
3359.2881430.8443500.9021432.2713750.9141400.6443840.9181362.8773940.9231348.068
4060.9281315.8994850.9661298.296 5140.981306.2565180.9811318.8335410.9921315.313
5450.9941312.7715500.9971277.3845661.0041279.1715881.0151256.1686541.0461233.694
6691.0531212.0196721.0541226.2516881.0621228.4518297.2371232.8468415.9691231.464
8458.6221215.0319802.5021221.4049943.181 1214.549985.3851199.69510365.221224.845
10519.961225.10310662.341247.87811174.18 1293.0411406.241337.58511567.621327.932
#Mann= 3 , 0 , 0
3359.288  0.0507       03359.288  0.0507       011567.62  0.0507       0
#XS Ineff= 2 , 0
       09773.175                       0
Bank Sta=3359.288,11567.62
Exp/Cntr=0.3,0.1

Type RM Length L Ch R = 1 ,3572.997,150.998900,150.998900,150.998900
XS GIS Cut Line= 6
758734.016301811762689.839001551 760258.04721117762989.387237325
760855.253638089  763731.4597103761640.059444964764633.297962144
762042.837222695765011.770184353762692.142778307765768.714628816
#Sta/Elev= 30
5976.9041256.3376090.011 1254.026273.455 1233.036334.6031236.0926365.1771232.688
 6772.831228.0616793.2131220.0816833.9781218.5226874.7441206.792  6925.71222.157
7620.9331222.7527691.3331227.1847948.0571218.5619639.9631219.4459812.052 1222.97
9849.5811220.5629918.1911201.4429987.2911196.66410014.251198.452 10045.71209.237
 10110.31222.56210314.14 1228.5210372.39 1223.1410524.941235.26210630.341235.483
   107411246.68510893.84 1251.3710986.751263.12711186.421273.66111228.111291.646
#Mann= 3 , 0 , 0
5976.904    0.06       05976.904    0.06       011228.11    0.06       0
#XS Ineff= 2 , 0
       09696.848        10192.07       0
Bank Sta=5976.904,11228.11
Exp/Cntr=0.3,0.1

Type RM Length L Ch R = 3 ,3476.129,,,
BEGIN DESCRIPTION:
END DESCRIPTION:
Bridge Culvert--1,0,-1,-1, 0
Deck Dist Width WeirC Skew NumUp NumDn MinLoCord MaxHiCord MaxSubmerge Is_Ogee
58.603150,33.792600,2.6,0, 60, 60, , , 0.95, 0, 0,0,,
 9168.90 9245.56 9259.95 9320.60 9405.21 9498.34 9532.86 9548.02 9593.51 9623.83
 9631.38 9669.57 9702.17 9767.37 9783.67 9835.65 9873.73 9873.7310126.0210126.02
10153.3210158.3910161.4710173.0610187.7410202.4710217.0810229.8010270.8010305.11
10380.1310393.7910434.7910451.8310462.1210481.1710489.4610495.8410502.9710516.04
10529.1010568.2810588.8710604.4210619.9610651.0510672.7810713.2210728.7610759.85
10764.2210816.5310855.8110914.8710961.3410986.7411052.2111065.3011100.7711148.74
 1219.40 1219.63 1219.79 1220.10 1220.81 1221.11 1220.99 1221.16 1221.44 1221.86
 1221.89 1222.35 1222.61 1222.84 1223.03 1223.33 1223.66 1223.66 1224.05 1224.05
 1224.10 1225.63 1226.02 1226.34 1226.45 1226.67 1226.95 1227.31 1228.64 1230.11
 1234.32 1235.20 1237.43 1238.64 1239.12 1240.40 1241.35 1241.72 1241.99 1242.78
 1243.73 1246.17 1247.68 1248.90 1250.22 1252.56 1254.02 1256.95 1257.93 1260.25
 1260.48 1264.32 1267.05 1271.39 1274.60 1276.14 1280.71 1281.55 1284.32 1287.82
  219.40  219.63  219.79  220.10  220.81  221.11  220.99  221.16  221.44  221.86
  221.89  222.35  222.61  222.84  223.03  223.33  223.66 1219.66 1220.05  224.05
  224.10  225.63  226.02  226.34  226.45  226.67  226.95  227.31  228.64  230.11
  234.32  235.20  237.43  238.64  239.12  240.40  241.35  241.72  241.99  242.78
  243.73  246.17  247.68  248.90  250.22  252.56  254.02  256.95  257.93  260.25
  260.48  264.32  267.05  271.39  274.60  276.14  280.71  281.55  284.32  287.82
 9168.90 9245.56 9259.95 9320.60 9405.21 9498.34 9532.86 9548.02 9593.51 9623.83
 9631.38 9669.57 9702.17 9767.37 9785.00 9848.31 9864.96 9878.11 9878.1110130.40
10130.4010153.3210158.3910161.4710173.0610187.7410202.4710217.0810229.8010270.80
10305.1110380.1310393.7910434.7910451.8310462.1210481.1710489.4610495.8410502.97
10516.0410529.1010568.2810588.8710619.9610651.0510672.7810713.2210728.7610759.85
10764.2210816.5310855.8110914.8710961.3410986.7411052.2111065.3011100.7711148.74
 1219.40 1219.63 1219.79 1220.10 1220.81 1221.11 1220.99 1221.16 1221.44 1221.86
 1221.89 1222.35 1222.61 1222.84 1223.04 1223.43 1223.63 1223.64 1223.64 1224.06
 1224.06 1224.10 1225.63 1226.02 1226.34 1226.45 1226.67 1226.95 1227.31 1228.64
 1230.11 1234.32 1235.20 1237.43 1238.64 1239.12 1240.40 1241.35 1241.72 1241.99
 1242.78 1243.73 1246.17 1247.68 1250.22 1252.56 1254.02 1256.95 1257.93 1260.25
 1260.48 1264.32 1267.05 1271.39 1274.60 1276.14 1280.71 1281.55 1284.32 1287.82
  219.40  219.63  219.79  220.10  220.81  221.11  220.99  221.16  221.44  221.86
  221.89  222.35  222.61  222.84  223.04  223.43  223.63  223.64 1219.64 1220.06
  224.06  224.10  225.63  226.02  226.34  226.45  226.67  226.95  227.31  228.64
  230.11  234.32  235.20  237.43  238.64  239.12  240.40  241.35  241.72  241.99
  242.78  243.73  246.17  247.68  250.22  252.56  254.02  256.95  257.93  260.25
  260.48  264.32  267.05  271.39  274.60  276.14  280.71  281.55  284.32  287.82
Pier Skew, UpSta & Num, DnSta & Num=  ,9935.80, 2 ,9940.18, 2 , 0 , 0 , 0 ,,
    4.00    4.00
  223.73 1223.73
    4.00    4.00
  223.74 1223.74
Pier Skew, UpSta & Num, DnSta & Num=  ,9999.87, 2 ,10004.25, 2 , 0 , 0 , 0 ,,
    4.00    4.00
  223.84 1223.84
    4.00    4.00
  223.85 1223.85
Pier Skew, UpSta & Num, DnSta & Num=  ,10063.95, 2 ,10068.33, 2 , 0 , 0 , 0 ,,
    4.00    4.00
  223.95 1223.95
    4.00    4.00
  223.96 1223.96
BR Coef=-1 , 0 , 0 ,, 0 ,,,0.8,0,1,0,
WSPro=,,,, 1 ,,,, 0 ,,,, 0 ,,,,-1 ,-1 ,-1 , 0 , 0 , 0 , 0 , 0
BC Design=,, 0 ,, 0 ,,,,,,

Type RM Length L Ch R = 1 ,3421.998,1631.424200,1631.424200,1631.424200
XS GIS Cut Line= 6
758684.016301841762831.505668208760098.585405648763112.911542878
761000.090035319764151.800431758761671.309444964764852.047962144
761912.242813051765103.050431758762473.392778307765779.131295457
#Sta/Elev= 30
6062.3341248.983 6206.081244.4566328.4321233.1256613.9181227.4026746.5321215.729
6929.993 1214.966960.5811205.5127042.1491222.2147082.932 1215.957348.0271225.548
7600.0681223.044 7785.431230.059 7864.871214.7567944.3111211.9838036.9921224.949
8674.0041222.7878857.8781227.9698953.8151218.5169884.3241214.2779992.8191195.813
10028.731197.92810048.261207.96310115.371224.551 10421.51238.42510452.871248.095
10577.451251.34710828.651279.55510859.971288.06710953.911294.66311076.66 1291.87
#Mann= 3 , 0 , 0
6062.334  0.0445       06062.334  0.0445       011076.66  0.0445       0
#XS Ineff= 2 , 0
       09713.482        10210.92       0
Bank Sta=6062.334,11076.66
Exp/Cntr=0.3,0.1

Type RM Length L Ch R = 1 ,1790.574,711.142600,711.142600,711.142600
XS GIS Cut Line= 4
758442.717350066  763202.3675614759845.495127857763674.589783594
760477.439572334765591.256450281761148.348729318766883.007554306
#Sta/Elev= 30
7060.346 1254.847221.0261249.2547421.5031250.7437463.7081243.5698054.5871229.835
8286.7181210.2278328.924 1200.128350.0271216.0988392.2321222.7658476.6431221.926
8561.9651212.6758793.6151215.9848826.3141209.2439088.4421219.2099741.2721218.963
9772.8611225.2349825.5081213.1029899.2151213.7169962.3921201.8559983.4511191.787
10025.571191.58910057.161202.08210194.041201.88710246.69 1210.9810618.431228.737
10698.071238.57410833.29 1234.2911103.73 1239.4711700.951233.25512014.221238.453
#Mann= 3 , 0 , 0
7060.346    0.04       07060.346    0.04       012014.22    0.04       0
#XS Ineff= 2 , 0
       09691.968        10332.68       0
Bank Sta=7060.346,12014.22
Exp/Cntr=0.3,0.1

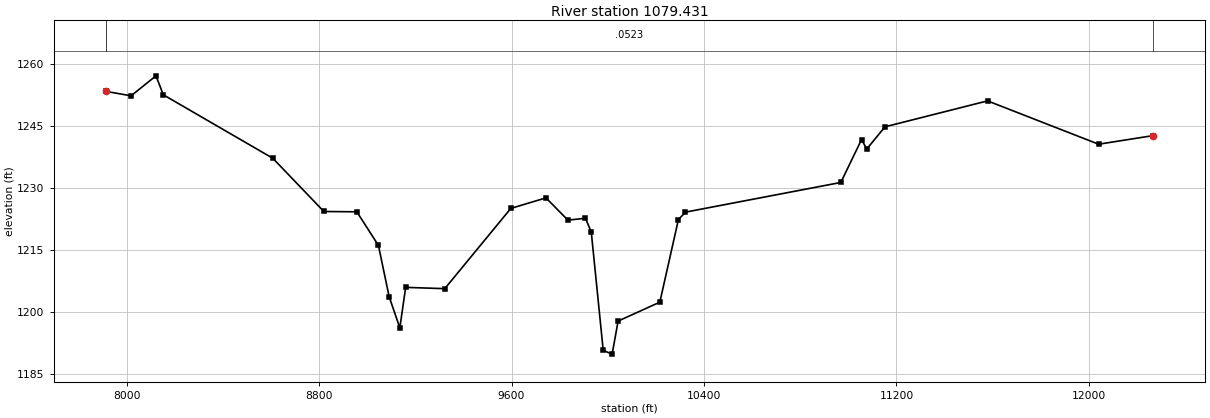
Type RM Length L Ch R = 1 ,1079.431,0.000000,0.000000,0.000000
XS GIS Cut Line= 6
758622.802041233763470.230986923758949.578997254763844.536767364
 759217.02084896764258.419543982759839.740540057 765432.51745607
760184.188981831766307.687410071760946.565322973 767086.69457769
#Sta/Elev= 30
7913.8511253.3618018.5431252.2828122.0561257.1248152.4631252.5328607.6891237.163
8819.9141224.2718956.9551224.1979046.6961216.0699091.238 1203.669135.7811196.084
9159.8831205.8999322.5181205.5859597.0341225.0169743.2671227.5739834.5591222.173
9907.4211222.6399931.564 1219.299981.2681190.62710018.371189.73310043.021197.734
10216.621202.31810293.791222.31710323.081224.11510968.951231.30411055.161241.703
11076.771239.40111152.421244.77611578.951251.05712040.681240.56112266.921242.647
#Mann= 3 , 0 , 0
7913.851  0.0523       07913.851  0.0523       012266.92  0.0523       0
#XS Ineff= 2 , 0
       09758.866        10367.92       0
Bank Sta=7913.851,12266.92
Exp/Cntr=0.3,0.1